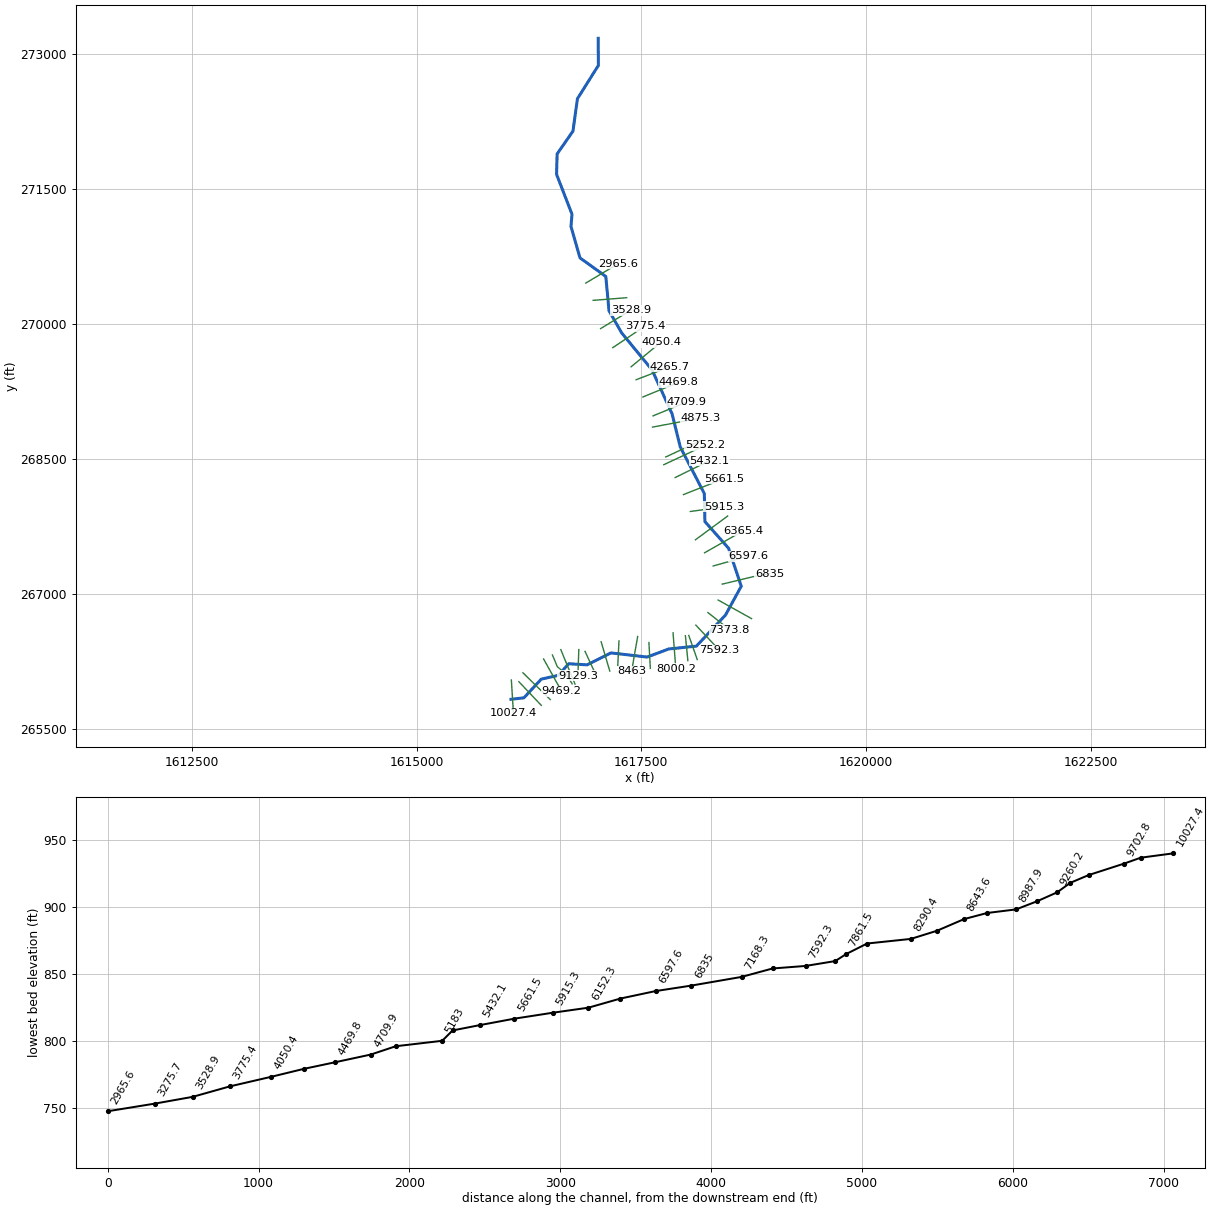
--- np5.prj (project) ---

Proj Title=np5
Current Plan=p01
Default Exp/Contr=0,0
English Units
Geom File=g01
Flow File=f01
Plan File=p01
BEGIN DESCRIPTION:
END DESCRIPTION:
DSS Export Rating Curves= 0
DSS Export Rating Curve Sorted= 0
DSS Export Volume Flow Curves= 0
DXF OffsetX= 0
DXF OffsetY= 0
DXF ScaleX= 0
DXF ScaleY= 0

--- np5.p01 (plan) ---

Plan Title=Approximate Study - 100yr
Program Version=4.00
Geom File=g01
Flow File=f01
Subcritical Flow
K Sum by GR= 0
Std Step Tol= 0.01
Critical Tol= 0.01
Num of Std Step Trials= 20
Max Error Tol= 0.3
Flow Tol Ratio= 0.001
Split Flow NTrial= 30
Split Flow Tol= 0.02
Split Flow Ratio= 0.02
Log Output Level= 0
Friction Slope Method= 1
Unsteady Friction Slope Method= 2
Unsteady Bridges Friction Slope Method= 1
Parabolic Critical Depth
Global Vel Dist= 0 , 0 , 0
Global Log Level= 0
CheckData=True
Encroach Param=-1 ,0,0, 0
Run HTab= 0
Run UNet= 0
Run PostProcess= 0
Run WQNet= 0
UNET Theta= 0
UNET Theta Warmup= 0
UNET ZTol= 0
UNET ZSATol= 0
UNET MxIter= 0
UNET MaxInSteps= 0
UNET DtIC= 0
UNET DtMin= 0
UNET MaxCRTS= 0
UNET WFStab= 0
UNET SFStab= 0
UNET WFX= 1
UNET SFX= 1
UNET DSS MLevel= 1
UNET DZMax Abort= 0
UNET Convert EG Bridges= 0
UNET Use Existing IB Tables= 0
UNET Froude Reduction=False
UNET Froude Limit= 0
UNET Froude Power= 0
UNET Time Slicing=0,0, 5
Write IC File= 0
Echo Input=False
Echo Output=False
Write Detailed= 0
Detailed Automatic Start=False, 0
WQ ULTIMATE=-1
WQ Max Comp Step=1HOUR
WQ Output Interval=15MIN
WQ Output Selected Increments= 0
WQ Output face flow=0
WQ Output face velocity=0
WQ Output face area=0
WQ Output face dispersion=0
WQ Output cell volume=0
WQ Output cell surface area=0
WQ Output cell continuity=0
WQ Output face conc=0
WQ Output face dconc_dx=0
WQ Output face courant=0
WQ Output face peclet=0
WQ Output face adv mass=0
WQ Output face disp mass=0
WQ Output cell mass=0
WQ Output cell source sink temp=0
WQ Output cell source sink nsm=0
WQ Output MaxMinRange=-1
WQ Daily Max Min Mean=-1
WQ Daily Range=0
WQ Daily Time=0
WQ Create Restart=0
WQ Fixed Restart=0
WQ System Summary=False
Sorting and Armoring Iterations= 10
XS Update Threshold= 0.02
Hydraulics Update Threshold= 0.02
Energy Slope Method= 1
Volume Change Method= 0
XS Weighting Method= 0
Number of US Weighted Cross Sections= 1
Number of DS Weighted Cross Sections= 1
Upstream XS Weight=0.25
Main XS Weight=0.5
Downstream XS Weight=0.25
Number of DS XS's Weighted with US Boundary= 1
Upstream Boundary Weight= 1
Weight of XSs Associated with US Boundary= 0
Number of US XS's Weighted with DS Boundary= 1
Downstream Boundary Weight= 0.5
Weight of XSs Associated with DS Boundary= 0.5
Sediment Output Level= 4
Mass or Volume Output= 0
Output Increment Type= 1
Profile and TS Output Increment= 10
XS Output Flag= 0
XS Output Increment= 10
Disregard all LS=0
Disregard all Conn=0
Disregard all Breaches=0
Disregard all Pumps=0

--- np5.f01 (steady flow) ---

Flow Title=USGS Regression Equation
Program Version=4.00
Number of Profiles= 1
Profile Names=P100yr
River Rch & RM=np5,Main            ,10027.4
     363
River Rch & RM=np5,Main            ,9347.1
     379
River Rch & RM=np5,Main            ,7373.8
     420
River Rch & RM=np5,Main            ,6597.6
     457
River Rch & RM=np5,Main            ,6152.3
     481
River Rch & RM=np5,Main            ,4469.8
     517
River Rch & RM=np5,Main            ,1499.1
     570
River Rch & RM=np5,Main            ,1175.2
     894
River Rch & RM=np5,Main            ,294.4
     902
Boundary for River Rch & Prof#=np5,Main            , 1
Up Type= 0
Dn Type= 3
Dn Slope=0.01507
DSS Import GetInterval= 0
DSS Import GetPeak= 0
DSS Import FillOption= 0

--- np5.g01 (geometry) ---

Geom Title=USGS 3m DEM
Program Version=4.00

River Reach=np5             ,Main
Reach XY= 30
     1616050.346      265830.719     1616194.289      265847.231
     1616387.054      266054.659     1616576.562      266097.053
     1616692.685       266225.99       1616897.1      266213.733
     1617162.223      266346.294     1617564.938      266300.297
     1617804.381      266390.117     1618113.249      266421.902
     1618436.074      266766.703     1618611.614      267087.475
     1618470.465      267509.837     1618207.564      267805.731
     1618201.196      268116.779     1617933.604      268635.186
     1617841.442      269005.096     1617619.226      269492.441
     1617281.554       269902.86     1617140.761      270150.174
     1617105.411      270530.183     1616818.826      270735.968
     1616717.827      271085.678     1616729.189      271222.027
     1616557.491      271665.161     1616563.803      271892.408
     1616739.758      272144.961     1616789.789      272505.978
     1617023.038       272876.21     1617020.133      273176.852

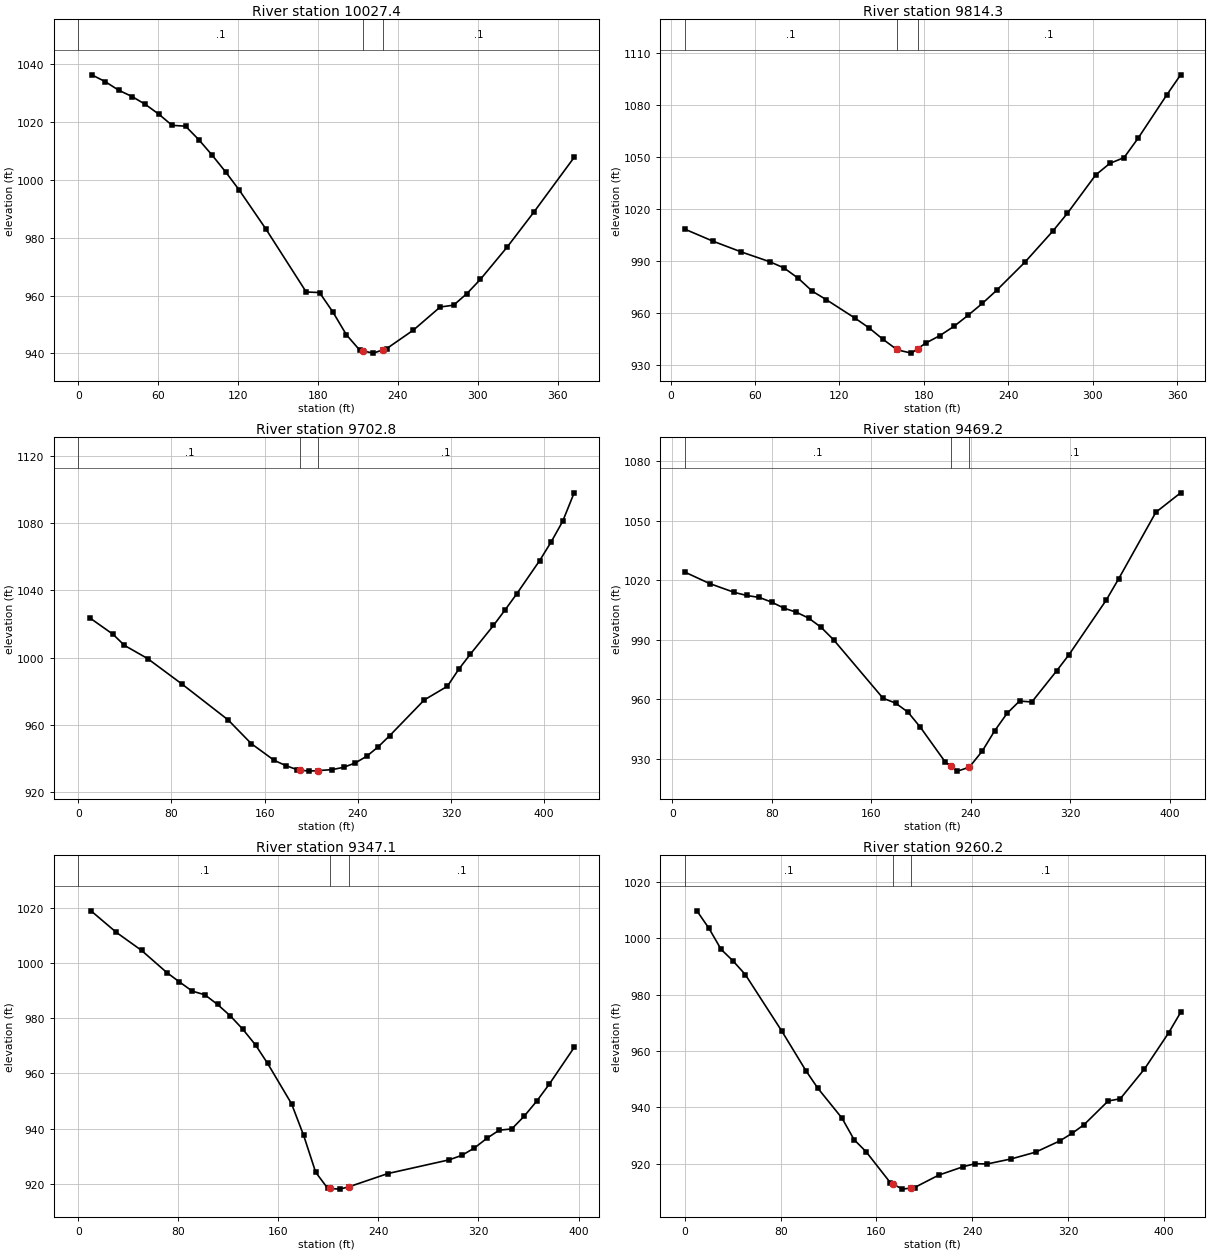
Type RM Length L Ch R = 1 ,10027.4 ,197.2,213.1,229
XS GIS Cut Line= 2
     1616054.751      266045.981     1616077.806      265674.371
#Sta/Elev= 30
    10.1 1036.37    20.1 1034.04    30.2 1031.07    40.3 1028.87    50.3 1026.15
    60.4 1022.77    70.4  1018.9    80.5 1018.61    90.6 1013.86   100.6 1008.51
   110.7 1002.73   120.8  996.52   140.9  982.99   171.1  961.26   181.1  961.06
   191.2  954.28   201.3  946.45   211.3  941.13   213.9  940.87   221.4  940.11
   228.9  941.25   231.4  941.63   251.6  948.08   271.7  956.06   281.8   956.7
   291.8  960.71   301.9  965.63     322   976.8   342.1  988.91   372.3 1007.82
#Mann= 3 , 0 , 0
       0      .1       0   213.9    .045       0   228.9      .1       0
Bank Sta=213.9,228.9
XS Rating Curve= 0 ,0
Exp/Cntr=0.3,0.1

Type RM Length L Ch R = 1 ,9814.3  ,110.7,111.5,112.2
XS GIS Cut Line= 2
     1616137.946       266026.69     1616387.382      265763.748
#Sta/Elev= 30
    10.1 1008.35    30.2 1001.39    50.3   995.2    70.5  989.57    80.5  986.03
    90.6  980.11   100.7  972.59   110.7  967.68   130.9  957.14   140.9  951.52
     151  944.81   160.6 939.079   161.1  938.78   171.1   936.9   175.6 939.456
   181.2  942.64   191.3  946.99   201.4  952.35   211.4  958.72   221.5  965.55
   231.6  973.04   251.7  989.26   271.8 1007.41   281.9 1017.44     302 1039.54
   312.1 1046.25   322.2 1049.57   332.2 1060.77   352.4 1085.53   362.4 1097.29
#Mann= 3 , 0 , 0
    10.1      .1       0   160.6    .045       0   175.6      .1       0
Bank Sta=160.6,175.6
XS Rating Curve= 0 ,0
Exp/Cntr=0.3,0.1

Type RM Length L Ch R = 1 ,9702.8  ,240.2,233.6,227
XS GIS Cut Line= 2
       1616183.2      266125.621     1616487.456      265827.725
#Sta/Elev= 30
     9.9 1023.57    29.7 1013.88    39.6 1007.24    59.4  999.43    89.1  984.18
   128.7  962.86   148.5   948.8   168.3  938.79   178.2  935.73   188.1  933.23
   190.6  933.03   198.1  932.43   205.6  932.73   217.9  933.32   227.8  934.69
   237.7  937.26   247.6  941.25   257.5  946.88   267.4  953.54   297.1  974.79
   316.9  982.91   326.8  993.15   336.7 1002.06   356.5 1019.09   366.4 1028.26
   376.3 1037.72   396.1 1057.61     406 1068.74   415.9 1080.99   425.8    1098
#Mann= 3 , 0 , 0
       0      .1       0   190.6    .045       0   205.6      .1       0
Bank Sta=190.6,205.6
XS Rating Curve= 0 ,0
Exp/Cntr=0.3,0.1

Type RM Length L Ch R = 1 ,9469.2  ,113.3,122.1,130.9
XS GIS Cut Line= 2
      1616413.18      266278.645      1616612.73      265922.072
#Sta/Elev= 30
      10  1024.1    29.9 1018.34    49.8 1013.88    59.8 1012.32    69.8 1011.35
    79.7 1009.01    89.7 1005.95    99.7 1003.88   109.6 1000.92   119.6  996.29
   129.6  990.04   169.4  960.58   179.4  958.17   189.4  953.61   199.3  946.06
   219.3  928.57   223.7 926.499   229.2  923.91   238.7 925.876   249.2  934.06
   259.1   944.2   269.1  953.01   279.1  959.18     289  958.72     309  974.43
   318.9  982.55   348.8    1010   358.8 1020.73   388.7 1054.21   408.6 1063.99
#Mann= 3 , 0 , 0
      10      .1       0   223.7    .045       0   238.7      .1       0
Bank Sta=223.7,238.7
XS Rating Curve= 0 ,0
Exp/Cntr=0.3,0.1

Type RM Length L Ch R = 1 ,9347.1  ,98,86.8,75.7
XS GIS Cut Line= 4
     1616511.706      266323.407     1616566.268      266192.686
     1616662.887      266113.117     1616731.089      266002.857
#Sta/Elev= 30
    10.1 1018.83    30.4 1011.03    50.6 1004.48    70.8  996.47    80.9  993.08
    91.1  989.76   101.2  988.43   111.3  984.94   121.4  980.86   131.5  975.98
   141.7  970.27   151.3  963.64   170.5  948.99   180.2  937.51   189.8  924.19
   199.4  918.38   201.5  918.31     209  918.08   216.5  918.94   247.6  923.73
   296.7   928.7   306.7  930.32   316.7  932.96   326.7  936.48   336.6  939.43
   346.6  939.86   356.6  944.51   366.5   949.9   376.5  956.02   396.5  969.37
#Mann= 3 , 0 , 0
       0      .1       0   201.5    .045       0   216.5      .1       0
Bank Sta=201.5,216.5
XS Rating Curve= 0 ,0
Exp/Cntr=0.3,0.1

Type RM Length L Ch R = 1 ,9260.2  ,140.7,131,121.3
XS GIS Cut Line= 2
     1616604.804      266382.669     1616762.536      265999.958
#Sta/Elev= 30
    10.1 1009.78    20.2 1003.54    30.3  996.11    40.4  991.94    50.5  987.16
    80.8  967.21     101   953.1   111.1  946.78   131.2  936.21   141.3  928.56
   151.4  924.24   171.6  913.26   174.2  912.68   181.7  910.99   189.2  911.41
   191.8  911.56     212  915.97   232.2  918.92   242.3  920.03   252.4  919.92
   272.6  921.73   292.8  924.11     313   928.1   323.1  930.75   333.2  933.83
   353.4  942.28   363.5  943.06   383.7  953.62   403.8   966.4   413.9  973.72
#Mann= 3 , 0 , 0
       0      .1       0   174.2    .045       0   189.2      .1       0
Bank Sta=174.2,189.2
XS Rating Curve= 0 ,0
Exp/Cntr=0.3,0.1

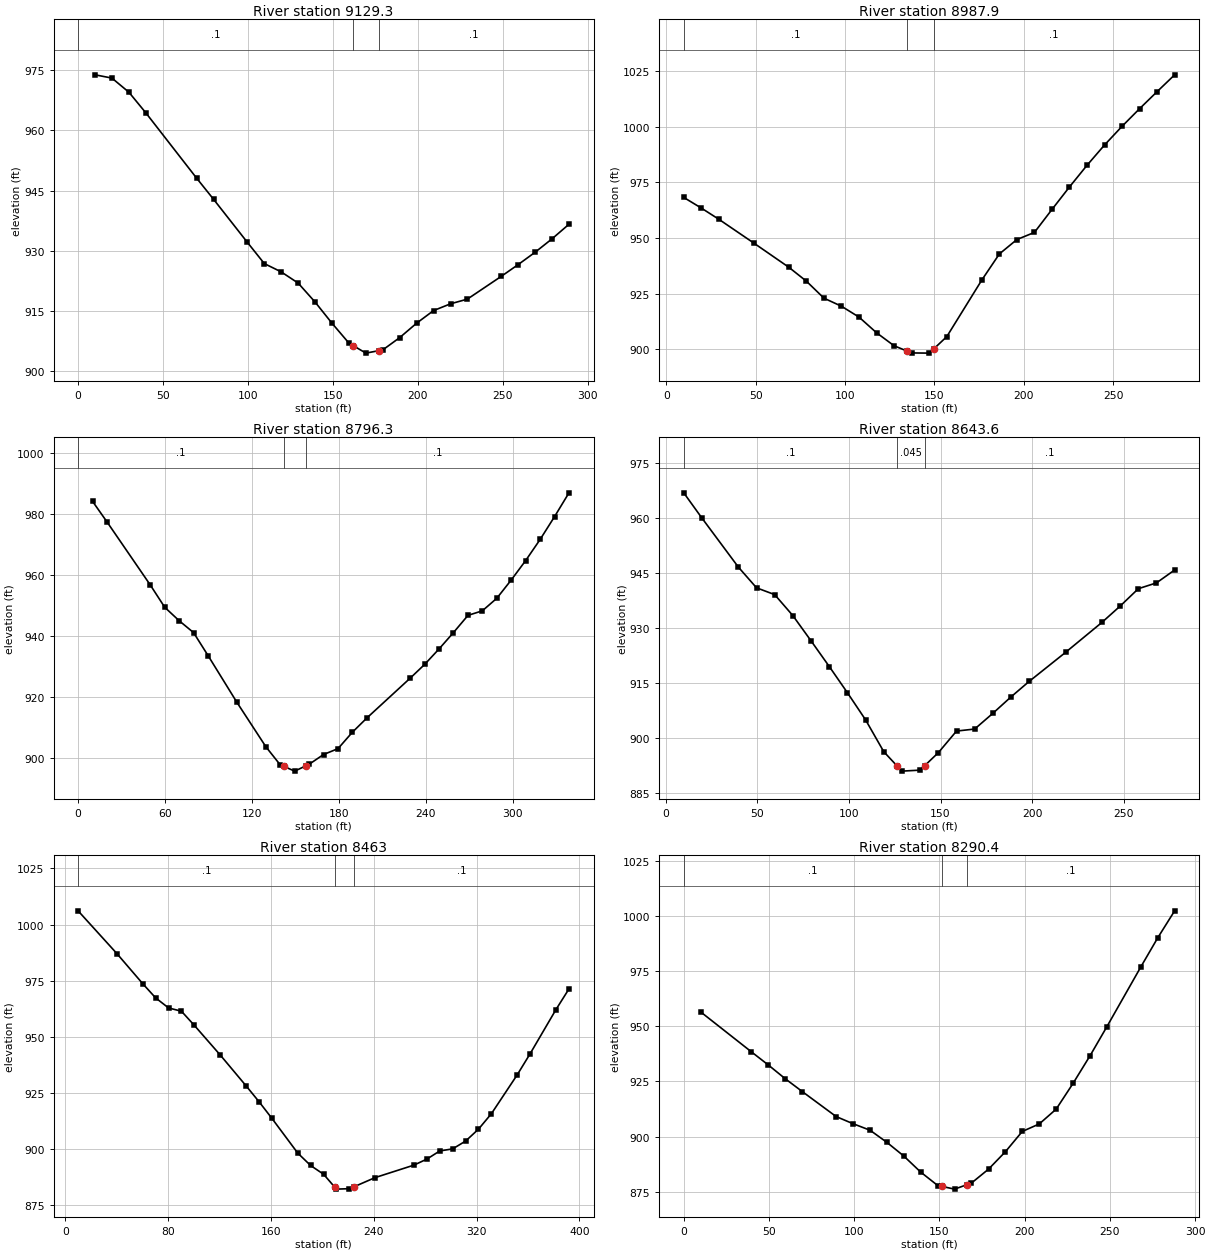
Type RM Length L Ch R = 1 ,9129.3  ,130.8,141.4,152
XS GIS Cut Line= 2
     1616804.975      266383.652     1616794.745       266094.93
#Sta/Elev= 27
      10  973.88    19.9  973.07    29.9  969.54    39.8  964.43    69.7  948.12
    79.7  942.83    99.6  932.08   109.6  926.76   119.5   924.7   129.5   921.9
   139.5  917.15   149.4  911.89   159.4  906.91   161.9  906.28   169.4  904.41
   176.9  905.02   179.3  905.21   189.3  908.29   199.2  911.87   209.2  915.03
   219.2  916.72   229.1  917.89   249.1  923.59     259  926.51     269   929.6
   278.9  932.93   288.9  936.58
#Mann= 3 , 0 , 0
       0      .1       0   161.9    .045       0   176.9      .1       0
Bank Sta=161.9,176.9
XS Rating Curve= 0 ,0
Exp/Cntr=0.3,0.1

Type RM Length L Ch R = 1 ,8987.9  ,194.8,191.5,188.2
XS GIS Cut Line= 2
     1616874.314      266363.191     1616993.667       266105.16
#Sta/Elev= 28
     9.8  968.27    19.6   963.5    29.4  958.46      49  947.73    68.6  936.83
    78.4  930.58    88.2  922.95      98  919.32   107.8  914.44   117.6   907.4
   127.4  901.55   134.6 899.177   137.2  898.32   147.1  898.23   149.6  900.13
   156.9  905.67   176.5  931.15   186.3  942.86   196.1  949.33   205.9  952.54
   215.7  962.86   225.5     973   235.3  982.73   245.1  991.87   254.9 1000.27
   264.7  1008.2   274.5 1015.87   284.3 1023.43
#Mann= 3 , 0 , 0
     9.8      .1       0   134.6    .045       0   149.6      .1       0
Bank Sta=134.6,149.6
XS Rating Curve= 0 ,0
Exp/Cntr=0.3,0.1

Type RM Length L Ch R = 1 ,8796.3  ,160.3,152.8,145.2
XS GIS Cut Line= 2
     1617053.494      266469.918     1617149.245      266144.901
#Sta/Elev= 30
      10  984.16    19.9  977.46    49.8  956.72    59.8  949.38    69.8  944.94
    79.7  941.06    89.7  933.51   109.6  918.17   129.6  903.57   139.5  897.63
     142  897.12   149.5  895.56     157  897.25   159.4  897.79   169.4  901.01
   179.4  902.95   189.3  908.33   199.3  913.01   229.2  926.09   239.2  930.61
   249.1  935.68   259.1  941.08   269.1  946.72     279  948.21     289  952.34
     299  958.37   308.9  964.72   318.9  971.66   328.9  979.19   338.8  986.97
#Mann= 3 , 0 , 0
       0      .1       0     142    .045       0     157      .1       0
Bank Sta=142,157
XS Rating Curve= 0 ,0
Exp/Cntr=0.3,0.1

Type RM Length L Ch R = 1 ,8643.6  ,183.3,180.5,177.8
XS GIS Cut Line= 2
     1617251.698      266480.271     1617238.058      266202.917
#Sta/Elev= 27
     9.9  966.85    19.8  959.98    39.7   946.6    49.6  940.96    59.5  939.11
    69.4   933.4    79.3  926.54    89.3   919.5    99.2  912.36   109.1  904.97
     119  896.31   126.4  892.34   128.9     891   138.8  891.27   141.4  892.51
   148.8  896.04   158.7  901.92   168.6  902.47   178.5  906.74   188.4  911.22
   198.3  915.44   218.2  923.37     238  931.52   247.9  935.95   257.9  940.72
   267.8  942.31   277.7  945.82
#Mann= 3 , 0 , 0
     9.9      .1       0   126.4    .045       0   141.4      .1       0
Bank Sta=126.4,141.4
XS Rating Curve= 0 ,0
Exp/Cntr=0.3,0.1

Type RM Length L Ch R = 1 ,8463    ,167.5,172.6,177.8
XS GIS Cut Line= 2
      1617459.52      266529.183     1617392.708      266143.055
#Sta/Elev= 30
      10 1006.11    40.2  987.07    60.3  973.67    70.3  967.38    80.4  962.88
    90.4  961.43   100.5  955.09   120.6  941.93   140.7  928.21   150.7   921.2
   160.8  913.73   180.9  898.28   190.9  892.76     201  888.86   209.5 883.234
     211  882.24   221.1  882.44   224.5 883.242   241.1  887.38   271.3  892.93
   281.3  895.59   291.4  899.24   301.4  900.15   311.5  903.64   321.5  908.93
   331.6  915.85   351.7  933.17   361.7  942.53   381.8  962.18   391.9  971.36
#Mann= 3 , 0 , 0
      10      .1       0   209.5    .045       0   224.5      .1       0
Bank Sta=209.5,224.5
XS Rating Curve= 0 ,0
Exp/Cntr=0.3,0.1

Type RM Length L Ch R = 1 ,8290.4  ,289.8,290.2,290.5
XS GIS Cut Line= 2
     1617584.751      266462.084     1617600.665      266174.499
#Sta/Elev= 27
     9.9  956.52    39.7   938.4    49.7  932.39    59.6  926.18    69.5  920.42
    89.4  909.07    99.3  905.83   109.3  902.87   119.2  897.36   129.1  891.17
     139   883.9     149  877.81   151.4  877.41   158.9  876.17   166.4  878.26
   168.8  878.93   178.8  885.22   188.7  893.12   198.6  902.31   208.6  905.73
   218.5  912.44   228.4  924.11   238.4  936.68   248.3  949.88   268.2  976.96
   278.1  990.12     288 1002.33
#Mann= 3 , 0 , 0
       0      .1       0   151.4    .045       0   166.4      .1       0
Bank Sta=151.4,166.4
XS Rating Curve= 0 ,0
Exp/Cntr=0.3,0.1

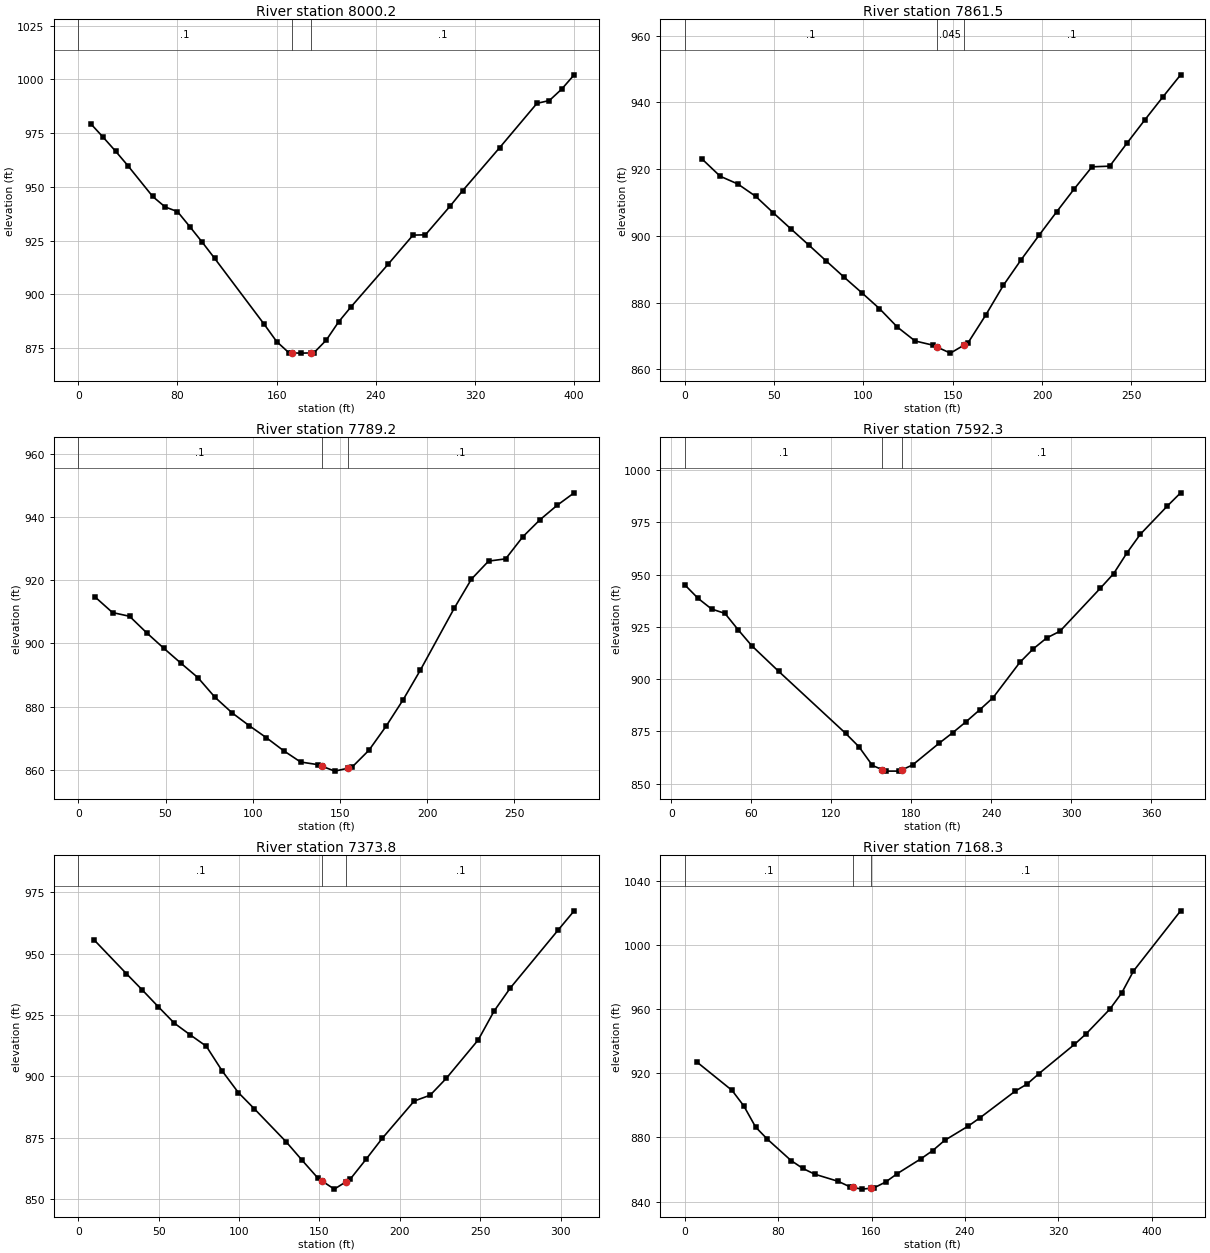
Type RM Length L Ch R = 1 ,8000.2  ,138.2,138.7,139.2
XS GIS Cut Line= 2
     1617853.119      266569.991     1617883.948      266171.196
#Sta/Elev= 30
      10  979.43      20  973.16      30  966.69      40  959.89      60  945.58
      70  940.72      80  938.54      90   931.5     100  924.29     110  916.78
     150  886.09     160   878.1     170  872.83   172.5   872.8     180  872.72
   187.5  872.82     190  872.85     200  878.76     210  887.27     220  894.25
     250  914.12     270  927.61     280  927.75     300  941.15     310  948.24
     340  968.36     370  988.91     380  990.21     390  995.56     400 1002.17
#Mann= 3 , 0 , 0
       0      .1       0   172.5    .045       0   187.5      .1       0
Bank Sta=172.5,187.5
XS Rating Curve= 0 ,0
Exp/Cntr=0.3,0.1

Type RM Length L Ch R = 1 ,7861.5  ,66.9,72.3,77.8
XS GIS Cut Line= 2
     1617990.553      266537.106     1618017.834      266260.888
#Sta/Elev= 30
     9.9  922.91    19.8  917.87    29.7  915.54    39.7  911.84    49.6  906.87
    59.5  902.04    69.4  897.25    79.3  892.41    89.2   887.6    99.1  882.94
     109  878.18     119  872.65   128.9  868.49   138.8  867.24   141.2  866.66
   148.7  864.84   156.2   867.2   158.6  867.95   168.5  876.26   178.4   885.2
   188.3  892.83   198.3  900.15   208.2  907.21   218.1  914.12     228  920.69
   237.9  920.89   247.8  927.95   257.7  934.86   267.6   941.6   277.6  948.27
#Mann= 3 , 0 , 0
       0      .1       0   141.2    .045       0   156.2      .1       0
Bank Sta=141.2,156.2
XS Rating Curve= 0 ,0
Exp/Cntr=0.3,0.1

Type RM Length L Ch R = 1 ,7789.2  ,187.4,196.9,206.3
XS GIS Cut Line= 2
     1618028.064      266540.516      1618122.41      266272.255
#Sta/Elev= 30
     9.8  914.57    19.6  909.74    29.4  908.56    39.2  903.34      49  898.46
    58.8  893.75    68.6  889.16    78.4  882.94    88.3  877.98    98.1  873.94
   107.9  870.15   117.7  866.08   127.5  862.48   137.3  861.66   139.6  861.18
   147.1   859.6   154.6  860.52   156.9  860.81   166.7  866.21   176.5  873.78
   186.3  882.16   196.1  891.46   215.7  911.19   225.5  920.33   235.3  926.01
   245.1  926.72     255  933.73   264.8  939.09   274.6  943.64   284.4   947.6
#Mann= 3 , 0 , 0
       0      .1       0   139.6    .045       0   154.6      .1       0
Bank Sta=139.6,154.6
XS Rating Curve= 0 ,0
Exp/Cntr=0.3,0.1

Type RM Length L Ch R = 1 ,7592.3  ,215.2,218.5,221.8
XS GIS Cut Line= 2
     1618107.016      266654.742     1618368.867      266376.637
#Sta/Elev= 30
    10.1  945.06    20.1  938.58    30.2  933.49    40.2  931.41    50.3  923.43
    60.3  915.95    80.4  903.76   130.7  874.04   140.7  867.62   150.8  858.68
   158.3  856.63   160.8  855.95   170.9  855.97   173.3 856.668   180.9  858.88
     201  869.37   211.1  874.35   221.1   879.6   231.2  885.22   241.3  891.08
   261.4  907.97   271.4  914.41   281.5  919.64   291.5  922.88   321.7  943.39
   331.7  950.37   341.8  960.41   351.8  969.28   371.9  982.68     382  989.08
#Mann= 3 , 0 , 0
    10.1      .1       0   158.3    .045       0   173.3      .1       0
Bank Sta=158.3,173.3
XS Rating Curve= 0 ,0
Exp/Cntr=0.3,0.1

Type RM Length L Ch R = 1 ,7373.8  ,201.9,205.6,209.2
XS GIS Cut Line= 2
     1618240.627      266795.137     1618482.744      266604.172
#Sta/Elev= 27
     9.9  955.54    29.8  941.91    39.8  935.19    49.7  928.39    59.7  921.68
    69.6  916.91    79.6  912.28    89.5  902.19    99.5  893.42   109.4  886.84
   129.3  873.31   139.3  865.73   149.2  858.41   151.7  857.32   159.2  854.06
   166.7  857.13   169.1  858.11   179.1  866.34     189  874.73   208.9  889.95
   218.8  892.32   228.8  899.15   248.7  914.83   258.6  926.61   268.6  935.94
   298.4  959.59   308.4  967.45
#Mann= 3 , 0 , 0
       0      .1       0   151.7    .045       0   166.7      .1       0
Bank Sta=151.7,166.7
XS Rating Curve= 0 ,0
Exp/Cntr=0.3,0.1

Type RM Length L Ch R = 1 ,7168.3  ,316.1,333.3,350.4
XS GIS Cut Line= 2
     1618354.843      266933.888     1618726.266      266727.644
#Sta/Elev= 30
    10.1  927.18    40.5  909.32    50.6  899.59    60.7  886.43    70.8  878.87
      91   865.6   101.2  860.63   111.3  857.07   131.5  852.59   141.6  849.14
   144.2  848.78   151.7  847.75   159.2  848.27   161.8  848.45     172  852.14
   182.1  857.44   202.3  866.67   212.4  871.79   222.5  878.09   242.8  887.06
   252.9  892.24   283.2  908.93   293.3   913.3   303.5  919.85   333.8  937.99
   343.9  944.66   364.2  960.04   374.3  970.07   384.4  983.78   424.8 1021.33
#Mann= 3 , 0 , 0
       0      .1       0   144.2    .045       0   159.2      .1       0
Bank Sta=144.2,159.2
XS Rating Curve= 0 ,0
Exp/Cntr=0.3,0.1

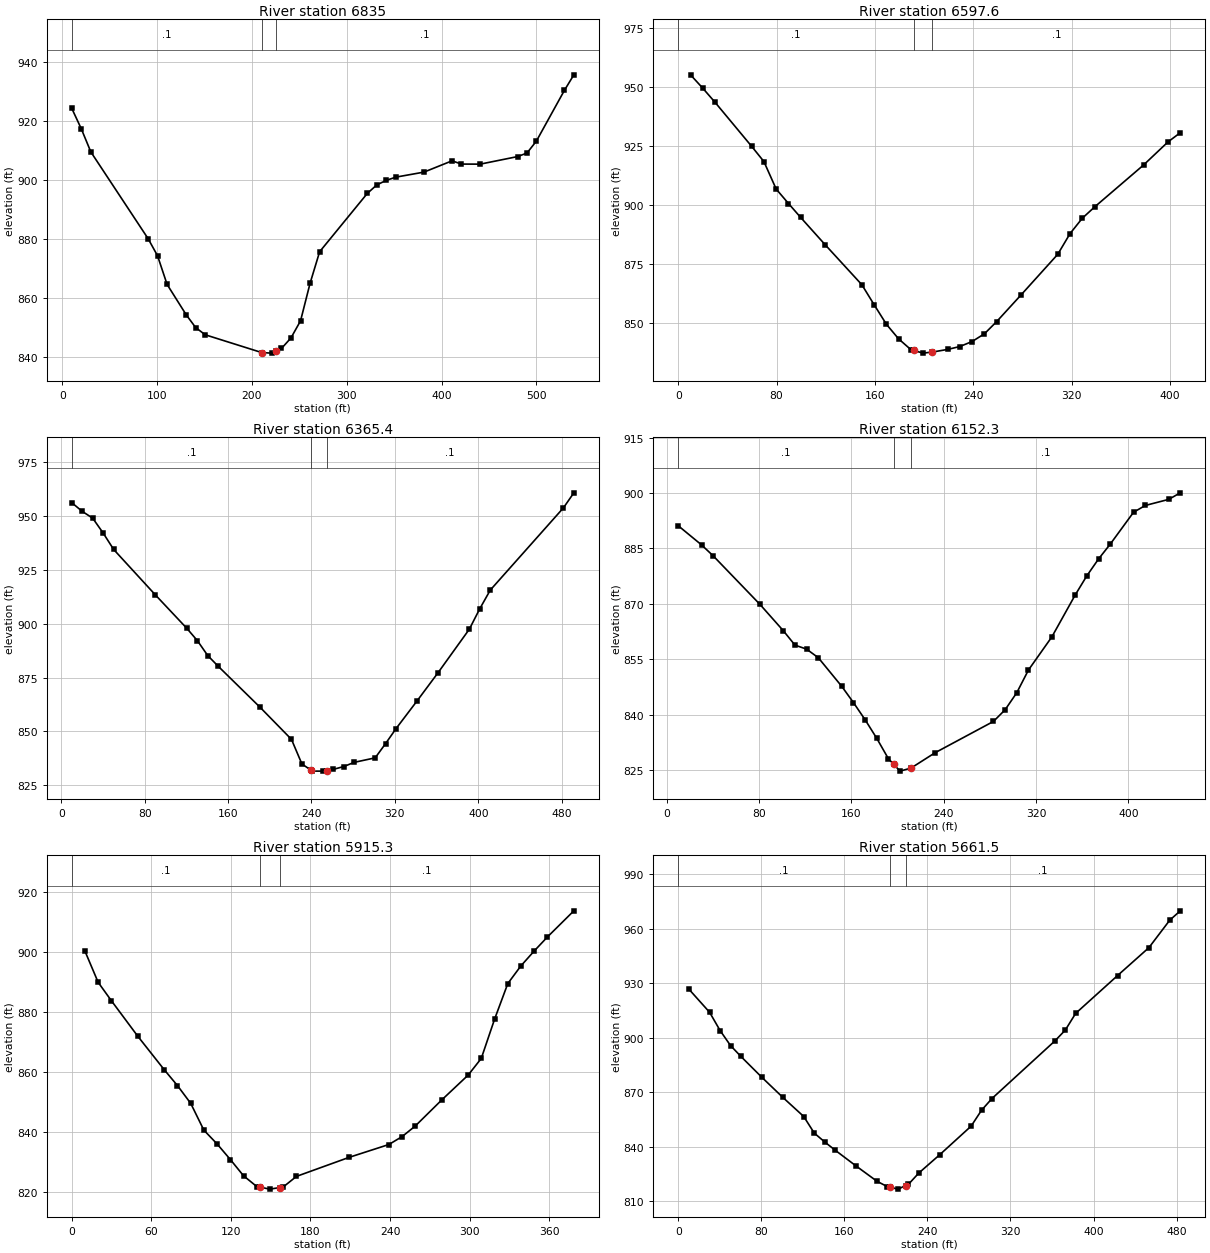
Type RM Length L Ch R = 1 ,6835    ,236.8,237.4,238
XS GIS Cut Line= 3
      1618400.73      267110.715      1618742.75      267193.156
      1618927.18      267227.152
#Sta/Elev= 30
    10.1  924.26    20.1  917.35    30.2  909.49    90.5  880.11   100.5  874.29
   110.6  864.55   130.7  854.28   140.7  849.93   150.8  847.48   210.6  841.43
   221.1  841.26   225.6 841.968   231.2  842.85   241.2  846.42   251.3  852.23
   261.3  864.92   271.4  875.64   321.7  895.43   331.7  898.31   341.8  899.86
   351.8  900.94   381.4  902.64     411  906.47   420.9  905.37   440.6  905.34
   480.1  907.91     490  909.11   499.9  913.16   529.5  930.39   539.4  935.63
#Mann= 3 , 0 , 0
    10.1      .1       0   210.6    .045       0   225.6      .1       0
Bank Sta=210.6,225.6
XS Rating Curve= 0 ,0
Exp/Cntr=0.3,0.1

Type RM Length L Ch R = 1 ,6597.6  ,226.7,232.2,237.7
XS GIS Cut Line= 2
     1618298.598      267312.336     1618691.896      267422.595
#Sta/Elev= 30
      10  955.28    19.9  949.64    29.9  943.65    59.8  924.88    69.7  918.46
    79.7  906.78    89.7  900.66    99.6  894.75   119.5  883.18   149.4  866.18
   159.4  857.68   169.4  849.38   179.3   843.2   189.3  838.63   191.7  838.27
   199.2  837.15   206.7   837.6   219.2  838.72   229.1  839.95   239.1  842.08
   249.1  845.35     259  850.49   278.9  861.84   308.8  879.11   318.8   887.9
   328.8  894.43   338.7  899.16   378.6     917   398.5  926.81   408.5  930.72
#Mann= 3 , 0 , 0
       0      .1       0   191.7    .045       0   206.7      .1       0
Bank Sta=191.7,206.7
XS Rating Curve= 0 ,0
Exp/Cntr=0.3,0.1

Type RM Length L Ch R = 1 ,6365.4  ,210.7,213.1,215.5
XS GIS Cut Line= 2
     1618203.964      267459.529     1618631.651      267702.224
#Sta/Elev= 30
      10  956.29    20.1  952.24    30.1  949.08    40.1   942.2    50.2  934.56
    90.3   913.4   120.4  897.91   130.5   892.2   140.5  885.24   150.5  880.29
   190.7  861.22   220.8  846.32   230.8   834.9   239.4 832.082   240.9  831.59
   250.9  831.58   254.4 831.865   260.9  832.39     271  833.72     281  835.66
   301.1  837.75   311.1  844.39   321.1  851.32   341.2  864.15   361.3  877.23
   391.4   897.5   401.4  906.96   411.5  915.67   481.7  953.89   491.7  960.87
#Mann= 3 , 0 , 0
      10      .1       0   239.4    .045       0   254.4      .1       0
Bank Sta=239.4,254.4
XS Rating Curve= 0 ,0
Exp/Cntr=0.3,0.1

Type RM Length L Ch R = 1 ,6152.3  ,248.3,236.9,225.5
XS GIS Cut Line= 2
     1618102.344      267603.607     1618460.499      267867.517
#Sta/Elev= 30
    10.1  891.16    30.3  885.97    40.4     883    80.9  869.86   101.1  862.74
   111.2  858.84   121.3  857.75   131.4  855.43   151.7  847.68   161.8   843.3
   171.9  838.66     182  833.62   192.1  828.09   196.7 826.563   202.2  824.73
   211.7 825.557   232.6  829.72   283.1  838.19   293.2  841.35   303.3  845.97
   313.4  852.11   333.7  861.09   353.9  872.43     364  877.63   374.1  882.17
   384.2  886.17   404.4  894.81   414.6  896.65   434.8  898.29   444.9  900.07
#Mann= 3 , 0 , 0
    10.1      .1       0   196.7    .045       0   211.7      .1       0
Bank Sta=196.7,211.7
XS Rating Curve= 0 ,0
Exp/Cntr=0.3,0.1

Type RM Length L Ch R = 1 ,5915.3  ,248.4,253.8,259.3
XS GIS Cut Line= 2
     1618045.114      267918.196     1618420.225      267969.348
#Sta/Elev= 30
      10  900.22    19.9  889.88    29.9  883.73    49.8   871.9    69.7  860.76
    79.7  855.46    89.7  849.53    99.6  840.61   109.6     836   119.6   830.8
   129.5  825.41   139.5  821.81   141.9   821.6   149.4  820.95   156.9  821.47
   159.4  821.65   169.4  825.19   209.2  831.55   239.1  835.82   249.1  838.46
     259  841.98     279  850.68   298.9  858.96   308.8  864.52   318.8  877.56
   328.8  889.47   338.7  895.37   348.7  900.32   358.7  905.01   378.6  913.71
#Mann= 3 , 0 , 0
       0      .1       0   141.9    .045       0   156.9      .1       0
Bank Sta=141.9,156.9
XS Rating Curve= 0 ,0
Exp/Cntr=0.3,0.1

Type RM Length L Ch R = 1 ,5661.5  ,227.6,229.4,231.2
XS GIS Cut Line= 2
     1617969.474      268106.187      1618419.51      268283.143
#Sta/Elev= 30
    10.1  926.87    30.2  914.03    40.3  903.97    50.4  895.66    60.4  889.66
    80.6  878.14   100.7  867.12   120.9  856.55     131  847.43     141  842.56
   151.1  838.01   171.3  829.28   191.4  820.87   201.5  817.85   204.1  817.51
   211.6  816.52   219.1  818.45   221.6   819.1   231.7  825.38   251.9   835.5
   282.1  851.24   292.2  860.05   302.2  866.48   362.7  898.18   372.8  904.19
   382.8  913.42   423.1  934.24   453.4  949.69   473.5  964.85   483.6  969.96
#Mann= 3 , 0 , 0
       0      .1       0   204.1    .045       0   219.1      .1       0
Bank Sta=204.1,219.1
XS Rating Curve= 0 ,0
Exp/Cntr=0.3,0.1

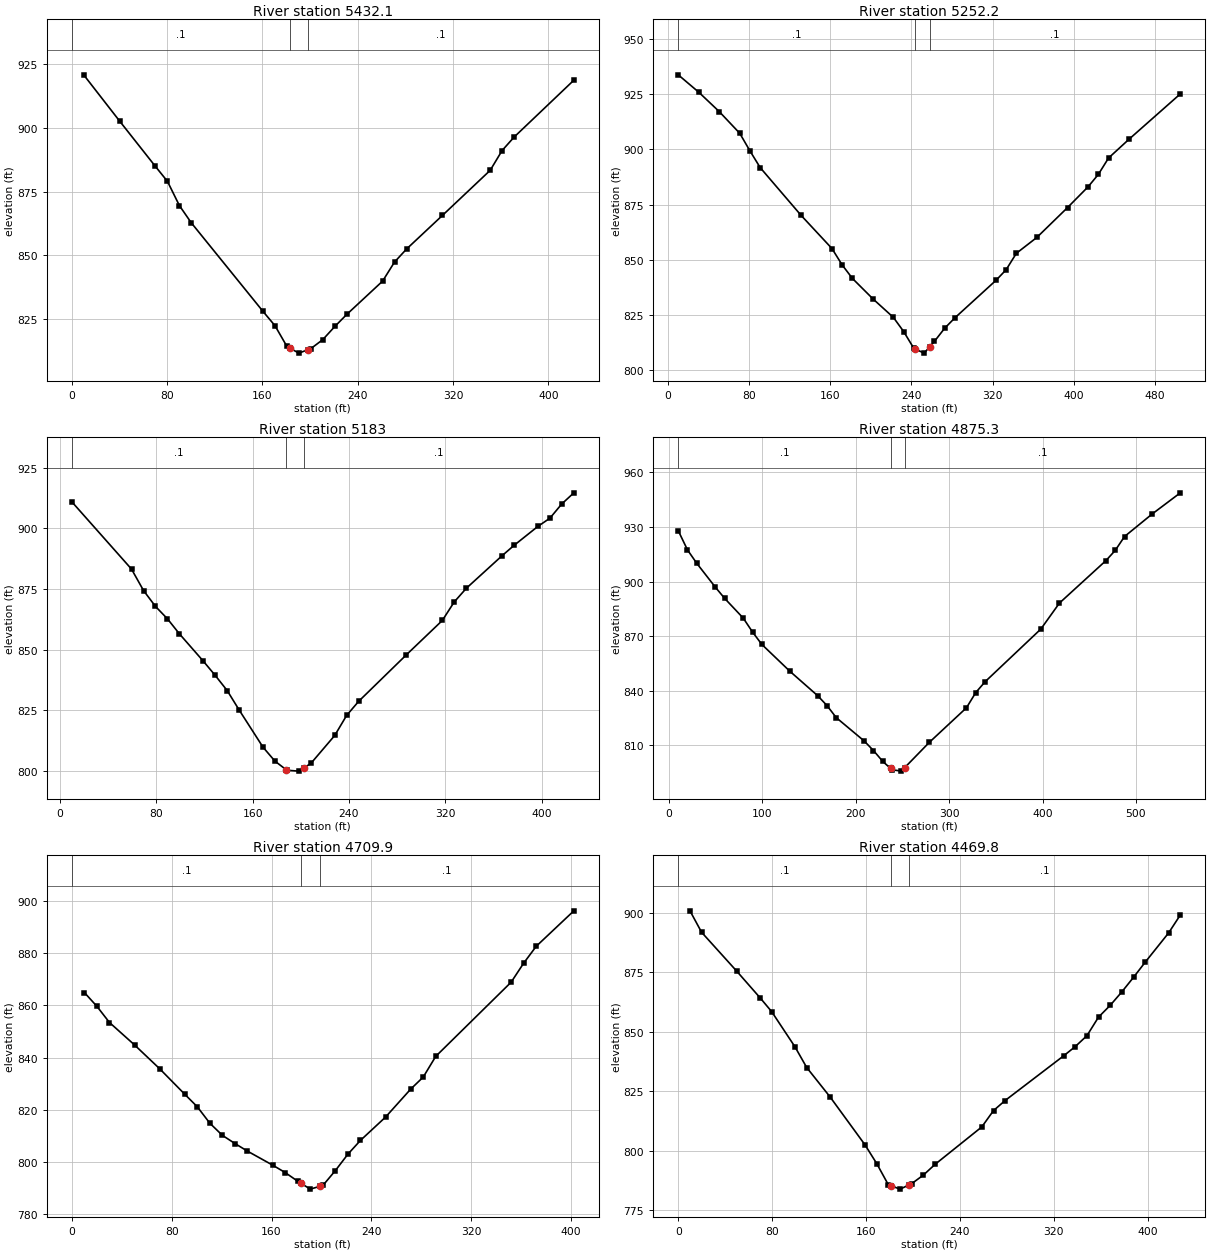
Type RM Length L Ch R = 1 ,5432.1  ,180.4,179.9,179.5
XS GIS Cut Line= 2
     1617876.883      268295.581     1618255.404      268480.863
#Sta/Elev= 24
      10  920.84    40.1  902.74    70.2  884.92    80.3  879.07    90.3  869.58
   100.3  862.81   160.5  828.06   170.6  822.42   180.6   814.3   183.1  813.65
   190.6  811.69   198.1  813.01   200.7  813.47   210.7  816.99   220.8  822.15
   230.8  826.87   260.9  839.94   270.9  847.42     281  852.52   311.1   865.7
   351.2  883.39   361.2  891.16   371.3  896.44   421.4  918.73
#Mann= 3 , 0 , 0
       0      .1       0   183.1    .045       0   198.1      .1       0
Bank Sta=183.1,198.1
XS Rating Curve= 0 ,0
Exp/Cntr=0.3,0.1

Type RM Length L Ch R = 1 ,5252.2  ,69.1,69.1,69.2
XS GIS Cut Line= 2
     1617750.381      268438.371     1618208.135      268651.657
#Sta/Elev= 30
    10.1   933.7    30.3  925.85    50.5  917.07    70.7  907.25    80.8  899.26
    90.9  891.69   131.3  870.03   161.6  855.08   171.7  847.64   181.8  841.53
     202  832.29   222.2  823.88   232.3  817.49   242.4  809.83     243 809.705
   252.5  807.72     258 810.602   262.6  813.02   272.7  818.97   282.8  823.69
   323.2  840.62   333.3  845.47   343.4  852.91   363.6   860.1   393.9  873.64
   414.1  883.02   424.2  888.63   434.3  896.06   454.5  904.57     505  925.06
#Mann= 3 , 0 , 0
    10.1      .1       0     243    .045       0     258      .1       0
Bank Sta=243,258
XS Rating Curve= 0 ,0
Exp/Cntr=0.3,0.1

Type RM Length L Ch R = 1 ,5183    ,313.5,307.8,302
XS GIS Cut Line= 2
     1617772.306      268524.057     1618158.784      268704.793
#Sta/Elev= 30
     9.9  910.97    59.5  883.21    69.5  874.36    79.4  867.83    89.3  862.74
    99.2  856.57   119.1  845.28     129   839.4   138.9  833.18   148.8   825.2
   168.7  809.81   178.6  804.07   187.9 800.547   188.5  800.32   198.4  799.97
   202.9 801.398   208.4  803.14   228.2  814.66   238.1  822.94   248.1  828.75
   287.7  847.91   317.5  862.04   327.4  869.68   337.4  875.29   367.1  888.72
     377  892.96   396.9  900.83   406.8  904.17   416.7  910.07   426.7  914.64
#Mann= 3 , 0 , 0
     9.9      .1       0   187.9    .045       0   202.9      .1       0
Bank Sta=187.9,202.9
XS Rating Curve= 0 ,0
Exp/Cntr=0.3,0.1

Type RM Length L Ch R = 1 ,4875.3  ,161,165.4,169.9
XS GIS Cut Line= 2
     1617624.528      268856.014     1618162.714      268956.633
#Sta/Elev= 30
      10  928.03    19.9  917.46    29.9  910.06    49.8  896.94    59.7  890.83
    79.6  879.99    89.6   872.3    99.5  865.53   129.4  850.84   159.3  837.34
   169.2  831.96   179.2  825.29     209  812.51     219  807.22     229  801.23
   237.4 797.361   238.9  796.67   248.9  795.91   252.4 797.805   278.7  811.67
   318.6  830.74   328.5  839.07   338.5  845.02   398.2  873.98   418.1  888.25
   467.9   911.6   477.8  917.18   487.8  924.82   517.6  937.29   547.5  948.83
#Mann= 3 , 0 , 0
      10      .1       0   237.4    .045       0   252.4      .1       0
Bank Sta=237.4,252.4
XS Rating Curve= 0 ,0
Exp/Cntr=0.3,0.1

Type RM Length L Ch R = 1 ,4709.9  ,240,240.1,240.2
XS GIS Cut Line= 2
     1617631.356      268981.011     1618003.057      269134.465
#Sta/Elev= 29
    10.1  864.93    20.1  859.66    30.2  853.46    50.3  844.86    70.4  835.76
    90.5     826   100.5  821.22   110.6  814.91   120.6  810.28   130.7  807.14
   140.7  804.23   160.9  798.87   170.9  796.04     181   792.7   183.5  791.95
     191  789.69   198.5  790.73   201.1  791.09   211.1  796.78   221.2   803.1
   231.2  808.34   251.3  817.26   271.4  827.95   281.5  832.59   291.5   840.5
   351.9   868.9   361.9  876.16     372  882.64   402.1   896.2
#Mann= 3 , 0 , 0
       0      .1       0   183.5    .045       0   198.5      .1       0
Bank Sta=183.5,198.5
XS Rating Curve= 0 ,0
Exp/Cntr=0.3,0.1

Type RM Length L Ch R = 1 ,4469.8  ,204.5,204.1,203.7
XS GIS Cut Line= 2
     1617517.451      269190.739     1617913.548      269352.509
#Sta/Elev= 30
      10  900.71    19.9  891.71    49.8   875.4    69.7  864.22    79.6   858.4
    99.5   843.6   109.5  834.91   129.4  822.57   159.2  802.43   169.2  794.55
   179.1  785.65   181.6   785.2   189.1  783.85   196.6   785.6     199  786.16
     209  789.78   218.9  794.26   258.7  809.97   268.7  816.83   278.6  821.06
   328.4  839.79   338.3  843.68   348.3  848.27   358.2  856.08   368.2  861.05
   378.1   866.7   388.1  872.84     398  879.16   417.9  891.41   427.9  898.96
#Mann= 3 , 0 , 0
       0      .1       0   181.6    .045       0   196.6      .1       0
Bank Sta=181.6,196.6
XS Rating Curve= 0 ,0
Exp/Cntr=0.3,0.1

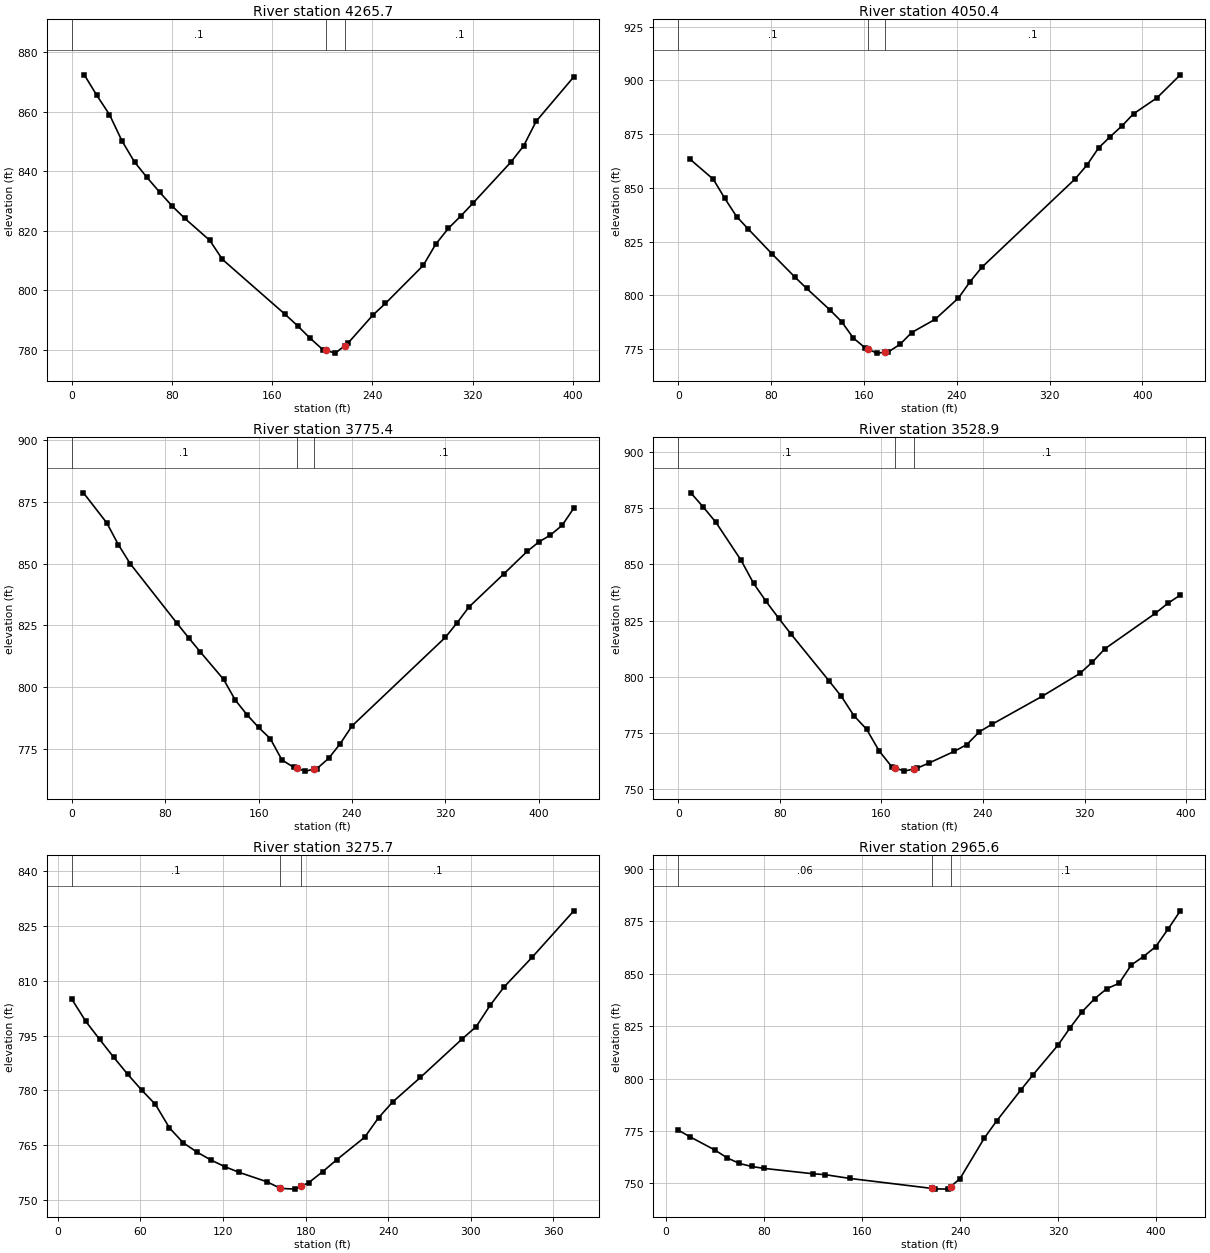
Type RM Length L Ch R = 1 ,4265.7  ,208,215.2,222.5
XS GIS Cut Line= 2
     1617442.663      269382.266     1617816.638      269526.626
#Sta/Elev= 30
      10  872.34      20  865.45    30.1  859.01    40.1  850.17    50.1   843.1
    60.1   837.9    70.2  832.96    80.2   828.3    90.2   824.2   110.2   816.8
   120.3  810.42   170.4  791.97   180.4  788.12   190.4  783.95   200.4  780.18
     203  779.87   210.5  778.98     218  781.47   220.5   782.3   240.5  791.77
   250.5  795.68   280.6  808.38   290.6  815.51   300.7  820.83   310.7     825
   320.7  829.45   350.8  843.14   360.8   848.5   370.8  856.75   400.9  871.68
#Mann= 3 , 0 , 0
       0      .1       0     203    .045       0     218      .1       0
Bank Sta=203,218
XS Rating Curve= 0 ,0
Exp/Cntr=0.3,0.1

Type RM Length L Ch R = 1 ,4050.4  ,277.4,275,272.7
XS GIS Cut Line= 2
     1617387.094      269526.714     1617721.177      269801.681
#Sta/Elev= 30
    10.1  863.32    30.2  853.97    40.2  845.01    50.3  836.61    60.4  830.78
    80.5  819.42   100.6  808.44   110.7  803.17   130.8  793.14   140.9  787.65
   150.9   780.1     161  775.58   163.6  774.94   171.1  773.08   178.6  773.51
   181.1  773.65   191.2   777.2   201.2  782.66   221.4  788.81   241.5  798.71
   251.6  806.37   261.6  812.98   342.1  854.14   352.2  860.53   362.2  868.49
   372.3  873.78   382.4  878.77   392.4  884.42   412.6  891.84   432.7  902.54
#Mann= 3 , 0 , 0
       0      .1       0   163.6    .045       0   178.6      .1       0
Bank Sta=163.6,178.6
XS Rating Curve= 0 ,0
Exp/Cntr=0.3,0.1

Type RM Length L Ch R = 1 ,3775.4  ,247.4,246.5,245.6
XS GIS Cut Line= 2
     1617183.348       269739.41     1617540.698      269978.617
#Sta/Elev= 30
      10  878.69      30  866.49      40   857.6      50     850      90  825.89
     100  819.98     110  814.26     130  803.09     140  794.71     150  788.79
     160   783.6     170  779.07     180  770.41     190  767.47   192.5  767.07
     200  765.89   207.5  766.65     210  766.91     220  771.07     230  777.06
     240   784.2     320  820.13     330     826     340  832.33     370  845.82
     390  854.94     400  858.77     410  861.59     420  865.53     430  872.52
#Mann= 3 , 0 , 0
       0      .1       0   192.5    .045       0   207.5      .1       0
Bank Sta=192.5,207.5
XS Rating Curve= 0 ,0
Exp/Cntr=0.3,0.1

Type RM Length L Ch R = 1 ,3528.9  ,263.8,253.1,242.5
XS GIS Cut Line= 2
     1617047.092      269950.615     1617384.692      270156.358
#Sta/Elev= 30
     9.9   881.8    19.8  875.41    29.7  868.66    49.4  851.89    59.3  841.59
    69.2  833.52    79.1  826.04      89  818.88   118.6   798.3   128.5  791.25
   138.4  782.67   148.3  776.72   158.1  767.17     168  760.09   170.4   759.6
   177.9  758.06   185.4     759   187.8   759.3   197.7  761.72   217.4  766.85
   227.3  769.88   237.2  775.59   247.1  778.89   286.6  791.34   316.3  801.48
   326.2  806.57     336  812.46   375.6  828.16   385.5  832.65   395.4  836.35
#Mann= 3 , 0 , 0
       0      .1       0   170.4    .045       0   185.4      .1       0
Bank Sta=170.4,185.4
XS Rating Curve= 0 ,0
Exp/Cntr=0.3,0.1

Type RM Length L Ch R = 1 ,3275.7  ,299.4,310.1,320.7
XS GIS Cut Line= 2
     1616964.343      270264.834     1617338.057      270294.282
#Sta/Elev= 30
    10.1  804.96    20.3  798.86    30.4  793.92    40.5  789.08    50.7   784.4
    60.8   780.1    70.9  776.13    81.1  769.71    91.2   765.6   101.3  763.04
   111.4  760.89   121.6  759.06   131.7  757.55     152  754.96   161.7 753.174
   172.2  752.96   176.7 753.758   182.4  754.77   192.5  757.76   202.6     761
   222.9  767.15     233   772.5   243.2  776.79   263.4  783.52   293.8  794.08
     304  797.45   314.1  803.28   324.2  808.28   344.5  816.37   374.9  829.12
#Mann= 3 , 0 , 0
    10.1      .1       0   161.7    .045       0   176.7      .1       0
Bank Sta=161.7,176.7
XS Rating Curve= 0 ,0
Exp/Cntr=0.3,0.1

Type RM Length L Ch R = 1 ,2965.6  ,213.5,221.9,230.3
XS GIS Cut Line= 2
     1616881.834      270456.694     1617242.604      270671.283
#Sta/Elev= 30
      10  775.42      20  772.11      40  765.91      50  762.18      60  759.52
      70  758.09      80  757.18   119.9  754.63   129.9  754.19   149.9  752.41
   217.4 747.615   219.9  747.42   229.9   747.3   232.4 748.533   239.9  752.23
   259.9   771.7   269.8  779.73   289.8  794.68   299.8  801.93   319.8   815.8
   329.8  824.17   339.8  831.92   349.8  838.02   359.8  842.83   369.8  845.39
   379.8  854.13   389.8  858.17   399.8   862.9   409.8  871.26   419.8  879.94
#Mann= 3 , 0 , 0
      10     .06       0   217.4    .045       0   232.4      .1       0
Bank Sta=217.4,232.4
XS Rating Curve= 0 ,0
Exp/Cntr=0.3,0.1