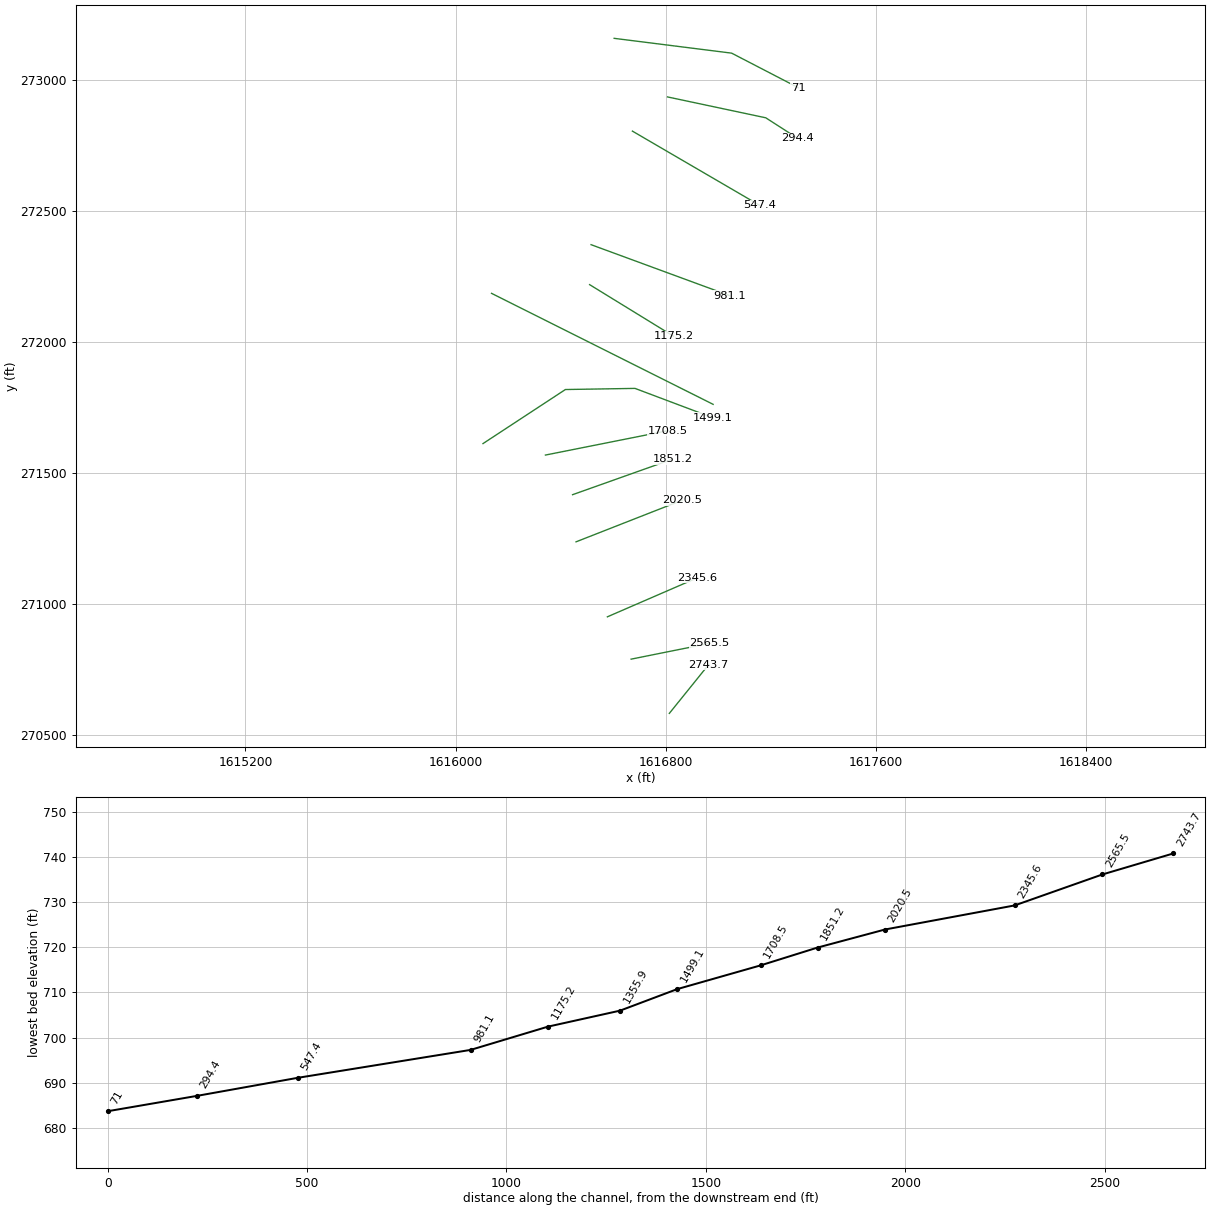
HEC-RAS study np5.prj: np5

--- np5.g01 (geometry) --- (continued)

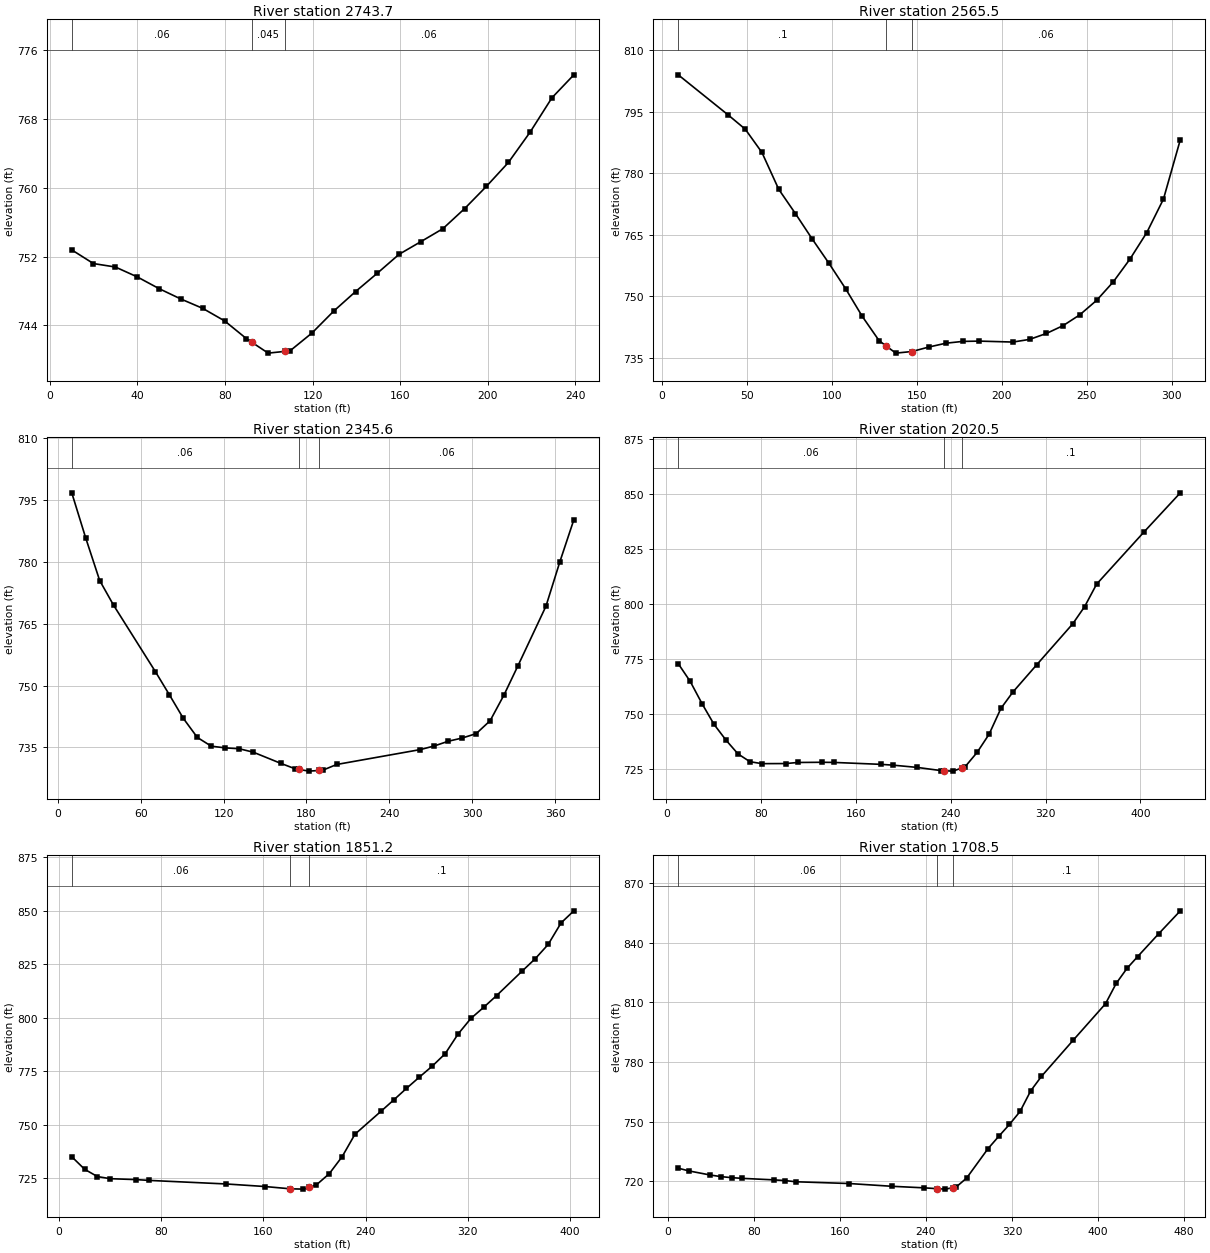
Type RM Length L Ch R = 1 ,2743.7  ,194,178.2,162.4
XS GIS Cut Line= 2
     1616814.068       270582.62     1616964.113      270769.039
#Sta/Elev= 26
      10  752.79    19.9   751.2    29.9   750.8    39.9  749.65    49.9  748.28
    59.8  747.08    69.8  745.99    79.8  744.53    89.7  742.48    92.2  742.05
    99.7  740.78   107.2  740.98   109.7  741.05   119.7  743.12   129.6  745.66
   139.6  747.94   149.6  750.09   159.5  752.28   169.5  753.76   179.5  755.26
   189.4  757.59   199.4  760.19   209.4  762.96   219.4  766.52   229.3  770.49
   239.3  773.16
#Mann= 3 , 0 , 0
      10     .06       0    92.2    .045       0   107.2     .06       0
Bank Sta=92.2,107.2
XS Rating Curve= 0 ,0
Exp/Cntr=0.3,0.1

Type RM Length L Ch R = 1 ,2565.5  ,215,219.9,224.8
XS GIS Cut Line= 2
     1616668.571        270789.5     1616967.523      270849.745
#Sta/Elev= 29
     9.8  803.97    39.3  794.14    49.2  790.72      59  785.05    68.9  776.05
    78.7  770.14    88.5  763.99    98.4  758.03   108.2  751.83     118  745.08
   127.9  739.16   132.2 737.821   137.7  736.12   147.2 736.513   157.4  737.63
   167.2  738.54   177.1  738.98   186.9  739.05   206.6  738.82   216.4  739.47
   226.3  740.92   236.1  742.83   245.9  745.46   255.8  748.99   265.6   753.5
   275.4  759.05   285.3  765.52   295.1  773.69     305  788.15
#Mann= 3 , 0 , 0
     9.8      .1       0   132.2    .045       0   147.2     .06       0
Bank Sta=132.2,147.2
XS Rating Curve= 0 ,0
Exp/Cntr=0.3,0.1

Type RM Length L Ch R = 1 ,2345.6  ,324.2,325.1,326
XS GIS Cut Line= 2
      1616578.24      270950.998     1616920.899      271099.864
#Sta/Elev= 30
    10.1  796.66    20.2  785.72    30.3  775.43    40.4  769.43    70.7  753.33
    80.8  747.74    90.9  742.03     101  737.43   111.1  735.31   121.2   734.9
   131.3  734.69   141.4  733.87   161.6  731.13   171.7  729.85   174.3   729.7
   181.8  729.27   189.3  729.43   191.8  729.49   201.9  730.88   262.5  734.49
   272.6  735.37   282.7  736.51   292.8  737.29   302.9  738.35     313  741.48
   323.1  747.76   333.2  754.83   353.4   769.2   363.5  779.99   373.6  790.14
#Mann= 3 , 0 , 0
    10.1     .06       0   174.3    .045       0   189.3     .06       0
Bank Sta=174.3,189.3
XS Rating Curve= 0 ,0
Exp/Cntr=0.3,0.1

Type RM Length L Ch R = 1 ,2020.5  ,170.4,169.3,168.1
XS GIS Cut Line= 2
     1616458.847      271237.058      1616862.39      271395.639
#Sta/Elev= 30
    10.1  772.78    20.2  764.72    30.3  754.48    40.3  745.19    50.4  738.02
    60.5  731.77    70.6  728.22    80.7  727.34   100.8  727.38   110.9  727.87
   131.1  727.96   141.2   727.9   181.5  727.01   191.6  726.64   211.8  725.62
   231.9  724.17   234.5  724.11     242  723.94   249.5  725.43   252.1  725.95
   262.2  732.45   272.3  740.71   282.3  752.47   292.4  759.89   312.6  772.36
   342.8  790.85   352.9  798.72     363  808.93   403.3  832.83   433.6  850.43
#Mann= 3 , 0 , 0
    10.1     .06       0   234.5    .045       0   249.5      .1       0
Bank Sta=234.5,249.5
XS Rating Curve= 0 ,0
Exp/Cntr=0.3,0.1

Type RM Length L Ch R = 1 ,1851.2  ,146,142.7,139.4
XS GIS Cut Line= 2
     1616445.778      271416.958     1616825.436      271552.225
#Sta/Elev= 30
    10.1  735.08    20.2   729.2    30.2   725.8    40.3  724.82    60.5  724.39
    70.5  724.02     131  722.35   161.2  721.16   180.9 720.098   191.4  719.94
   195.9 720.816   201.5  721.91   211.6  727.15   221.7  735.13   231.7   745.6
   251.9  756.23     262   761.6     272  767.02   282.1  772.29   292.2  777.44
   302.3  783.22   312.4  792.44   322.4  799.71   332.5  804.96   342.6  810.44
   362.7  821.95   372.8  827.65   382.9  834.31     393  844.38     403  850.03
#Mann= 3 , 0 , 0
    10.1     .06       0   180.9    .045       0   195.9      .1       0
Bank Sta=180.9,195.9
XS Rating Curve= 0 ,0
Exp/Cntr=0.3,0.1

Type RM Length L Ch R = 1 ,1708.5  ,213.5,209.4,205.3
XS GIS Cut Line= 2
     1616342.338      271568.139     1616809.522      271661.349
#Sta/Elev= 30
     9.9  726.55    19.8  725.17    39.7   723.1    49.6   722.3    59.5  721.77
    69.5  721.42    99.2  720.65   109.2  720.31   119.1  719.71   168.7  718.82
   208.4  717.43   238.2  716.65   250.5  716.23     258     716   265.5  716.75
     268     717   277.9   721.6   297.7  736.37   307.7  742.58   317.6  748.55
   327.5   755.1   337.4  765.49   347.4   772.8   377.1  791.13   406.9  809.35
   416.8  819.57   426.8  827.12   436.7  833.06   456.5  844.71   476.4  856.14
#Mann= 3 , 0 , 0
     9.9     .06       0   250.5    .045       0   265.5      .1       0
Bank Sta=250.5,265.5
XS Rating Curve= 0 ,0
Exp/Cntr=0.3,0.1

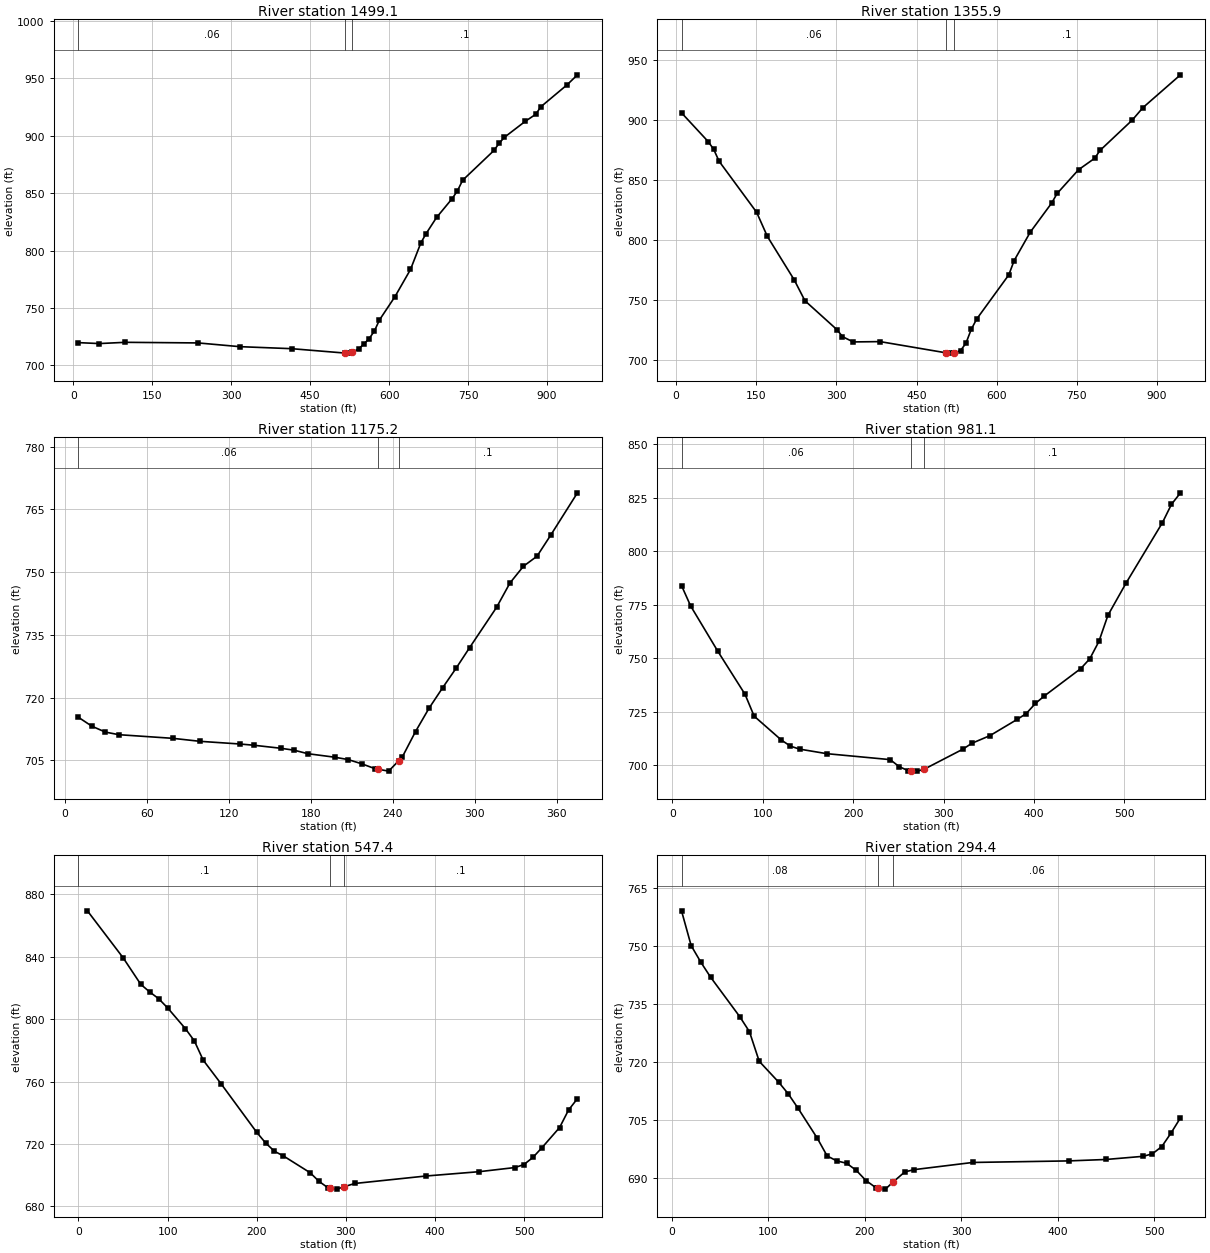
Type RM Length L Ch R = 1 ,1499.1  ,154.1,143.2,132.3
XS GIS Cut Line= 4
     1616104.586      271611.852     1616418.372      271818.147
     1616683.298       271822.49     1616979.978      271710.526
#Sta/Elev= 30
     9.9  719.87    49.4  719.06    98.8  720.15   237.2  719.61   316.2  716.37
   414.8  714.61   515.2  710.82   522.7  710.74   530.2  711.53   542.4  714.57
   552.2  718.74     562  723.39   571.8  729.85   581.6  739.65     611  759.89
   640.5  783.54   660.3   806.8   670.2  814.79     690   828.8   719.8  845.31
   729.7  852.05   739.6  861.23     799   887.1   808.9  893.42   818.9   898.6
   858.5  912.49   878.3  918.57   888.2   925.2   937.8  944.22   957.6  952.96
#Mann= 3 , 0 , 0
     9.9     .06       0   515.2    .045       0   530.2      .1       0
Bank Sta=515.2,530.2
XS Rating Curve= 0 ,0
Exp/Cntr=0.3,0.1

Type RM Length L Ch R = 1 ,1355.9  ,182.6,180.7,178.7
XS GIS Cut Line= 2
     1616137.159      272185.135     1616980.797      271761.687
#Sta/Elev= 30
      10  906.25    60.3   882.1    70.3  875.76    80.3  865.93   150.6  823.36
   170.7  803.22   220.9  767.08     241  749.64   301.3  725.39   311.3   719.7
   331.4  715.31   381.6  715.58   504.6  706.27   512.1  705.98   519.6  706.16
   532.2  708.09   542.3  714.17   552.3  725.79   562.4  734.34   622.6  771.21
   632.6  783.13   662.8  806.83   702.9  831.11     713  839.04   753.1  858.82
   783.3  868.37   793.3  874.91   853.6  900.19   873.7  910.61   943.9  937.93
#Mann= 3 , 0 , 0
      10     .06       0   504.6    .045       0   519.6      .1       0
Bank Sta=504.6,519.6
XS Rating Curve= 0 ,0
Exp/Cntr=0.3,0.1

Type RM Length L Ch R = 1 ,1175.2  ,189.5,194.1,198.8
XS GIS Cut Line= 2
      1616510.57      272218.331     1616829.982      272021.682
#Sta/Elev= 30
     9.9   715.3    19.7  713.18    29.6  711.77    39.5  711.15      79  710.28
    98.7  709.57   128.3  708.92   138.2  708.63   157.9  707.91   167.8  707.44
   177.7  706.61   197.4  705.77   207.3   705.2   217.2  704.19     227  703.02
   229.4  702.88   236.9  702.44   244.4  704.95   246.8  705.75   256.6  711.91
   266.5  717.49   276.4  722.36   286.3  727.05   296.1  731.93   315.9  741.59
   325.7  747.42   335.6  751.43   345.5  753.82   355.4  758.79   375.1  768.98
#Mann= 3 , 0 , 0
     9.9     .06       0   229.4    .045       0   244.4      .1       0
Bank Sta=229.4,244.4
XS Rating Curve= 0 ,0
Exp/Cntr=0.3,0.1

Type RM Length L Ch R = 1 ,981.1   ,437.8,433.7,429.6
XS GIS Cut Line= 2
      1616516.09        272370.8     1617043.772      272176.449
#Sta/Elev= 30
      10  783.97    20.1  774.45    50.2  753.27    80.3  733.18    90.4  722.97
   120.5  711.82   130.5  708.97   140.6  707.58   170.7  705.45     241  702.66
     251  699.36   261.1  697.47   263.6  697.42   271.1  697.29   278.6  698.18
   321.3  707.51   331.4   710.3   351.5  713.89   381.6  721.47   391.6  724.19
   401.7  728.89   411.7  732.43   451.9  745.18   461.9  749.75     472  757.86
     482  770.08   502.1  785.16   542.3  813.34   552.3   821.9   562.3   827.3
#Mann= 3 , 0 , 0
      10     .06       0   263.6    .045       0   278.6      .1       0
Bank Sta=263.6,278.6
XS Rating Curve= 0 ,0
Exp/Cntr=0.3,0.1

Type RM Length L Ch R = 1 ,547.4   ,245.5,252.9,260.3
XS GIS Cut Line= 2
     1616673.526       272804.02     1617156.691      272521.722
#Sta/Elev= 30
      10  869.52      50  839.47    69.9  822.36    79.9   817.5    89.9  813.19
    99.9  807.34   119.9  793.98   129.9  786.19   139.9  773.77   159.9  758.66
   199.9  727.52   209.8  720.76   219.8  715.37   229.8   712.4   259.8  701.63
   269.8  696.07   279.8  691.98   282.3  691.76   289.8  691.11   297.3  692.54
   309.8  694.73   389.7  699.52   449.7  702.31   489.6  704.96   499.6  706.88
   509.6   711.4   519.6  717.55   539.6  730.61   549.6   741.8   559.6  749.12
#Mann= 3 , 0 , 0
       0      .1       0   282.3    .045       0   297.3      .1       0
Bank Sta=282.3,297.3
XS Rating Curve= 0 ,0
Exp/Cntr=0.3,0.1

Type RM Length L Ch R = 1 ,294.4   ,221.6,223.4,225.2
XS GIS Cut Line= 3
     1616807.248      272934.452     1617181.223      272854.883
     1617302.849      272776.451
#Sta/Elev= 30
    10.1   759.2    20.1  750.18    30.2  745.86    40.2  742.02    70.4   731.8
    80.5  727.89    90.6  720.23   110.7  714.84   120.7  711.79   130.8  708.08
   150.9  700.25     161   695.7     171  694.42   181.1  693.82   191.2  691.97
   201.2  689.34   211.3  687.52   213.9  687.42   221.4  687.11   228.9  688.86
   241.5  691.58   251.5  692.17   311.9  694.02   411.3  694.42   449.9  694.79
   488.5  695.61   498.1  696.27   507.8  698.15   517.4  701.67   527.1  705.58
#Mann= 3 , 0 , 0
    10.1     .08       0   213.9    .045       0   228.9     .06       0
Bank Sta=213.9,228.9
XS Rating Curve= 0 ,0
Exp/Cntr=0.3,0.1

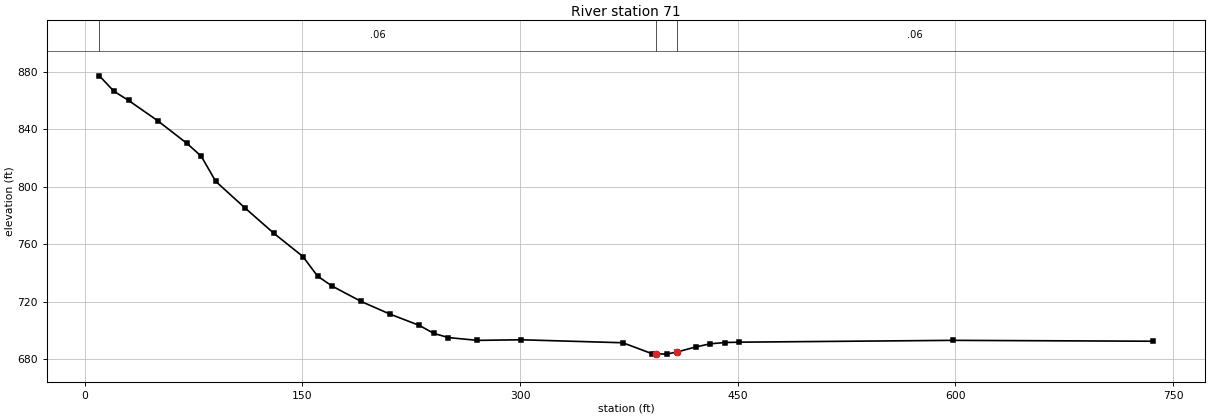
Type RM Length L Ch R = 1 ,71      ,73.1,71,68.9
XS GIS Cut Line= 3
      1616603.94      273158.024     1617051.372      273101.519
     1617304.355      272970.142
#Sta/Elev= 30
      10  877.04      20  866.37    30.1  859.96    50.1  845.94    70.2  830.24
    80.2  821.24    90.2  803.73   110.2  785.42   130.3  767.64   150.3  751.51
   160.4   737.9   170.4  731.01   190.4  720.32   210.5  711.43   230.5   703.7
   240.5  698.13   250.5  695.23   270.6  693.27   300.7  693.69   370.8  691.62
   390.9  684.01   393.4  683.94   400.9  683.72   408.4  685.26   420.9  688.68
   430.9  690.86     441  691.79     451  692.02   598.4  693.29     736  692.68
#Mann= 3 , 0 , 0
      10     .06       0   393.4    .045       0   408.4     .06       0
Bank Sta=393.4,408.4
XS Rating Curve= 0 ,0
Exp/Cntr=0.3,0.1

Chan Stop Cuts=-1
Use User Specified Reach Order=0